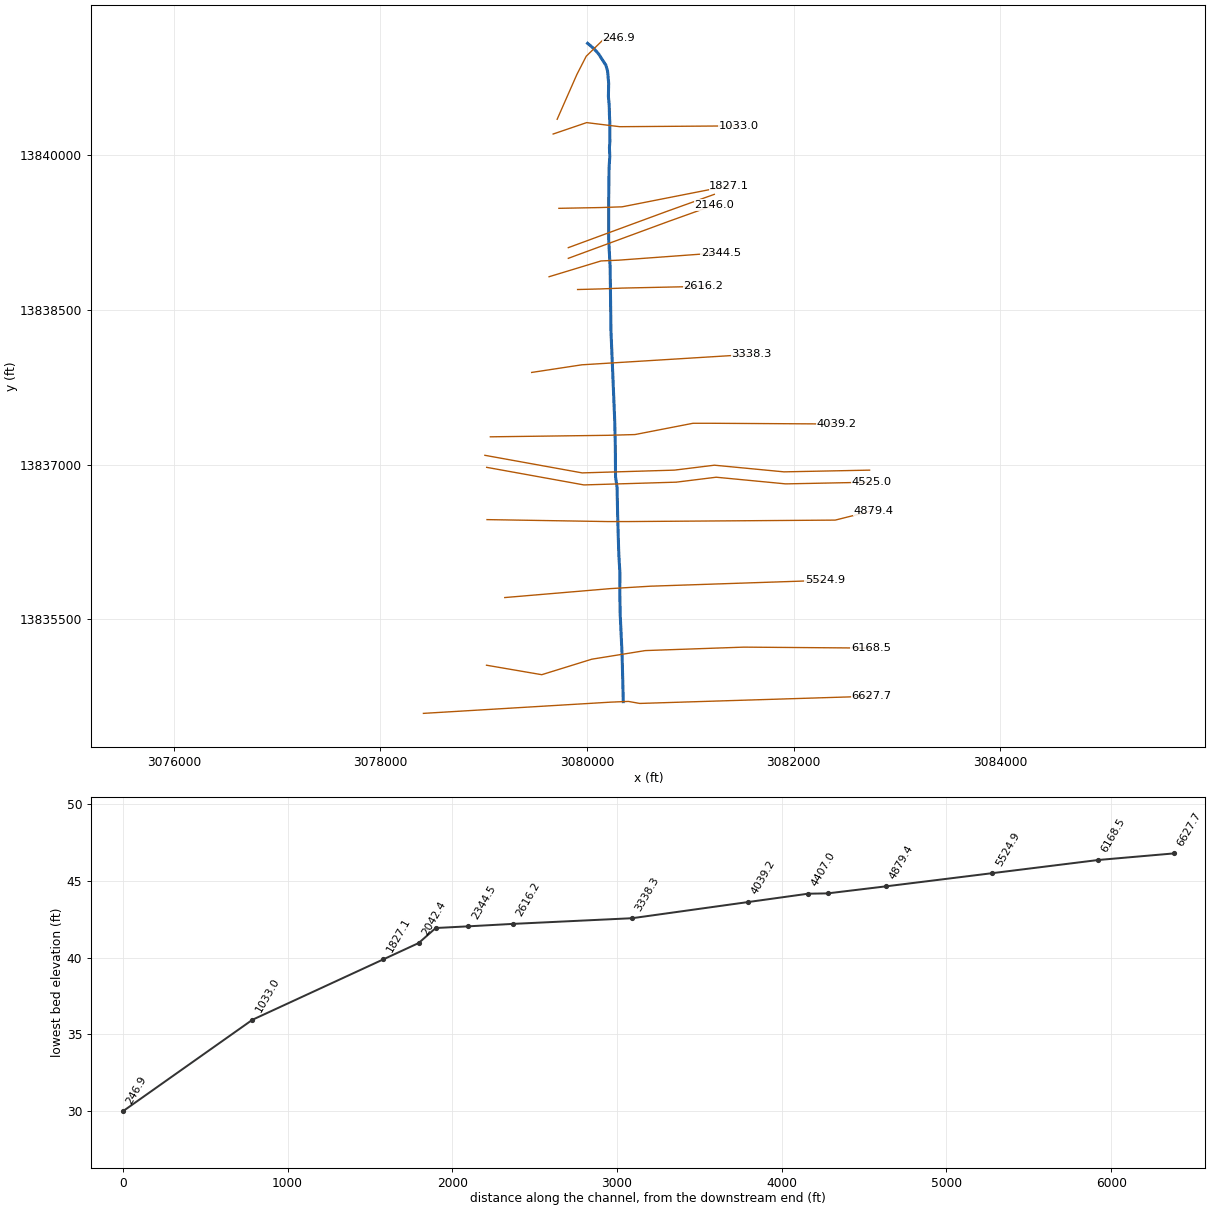
--- W142-00-00.PRJ (project) ---

Proj Title=W142-00-00
Current Plan=p01
Default Exp/Contr=.3,.1
English Units
Geom File=g01
Flow File=f01
Flow File=f03
Plan File=p01
Plan File=p03
Y Axis Title=Elevation
X Axis Title(PF)=Main Channel Distance
X Axis Title(XS)=Station
BEGIN DESCRIPTION:
Buffalo Bayou Watershed
Bering Ditch
HCFCD Unit W142-00-00
Flood Hazard Model
10, 2, 1, 0.2% Event
Filename W142-00-00.prj
Prepared by:  Watershed Concepts  Date:
Reviewed by:                      Date:
STATUS FINAL
END DESCRIPTION:
DSS File=dss
DSS Export Rating Curves= 0
DSS Export Rating Curve Sorted= 0
DSS Export Volume Flow Curves= 0
DXF OffsetX= 0
DXF OffsetY= 0
DXF ScaleX= 1
DXF ScaleY= 10

--- W142-00-00.p01 (plan) ---

Plan Title=FEMA Effective June 2007
Program Version=3.13
Short Identifier=FEMAeff0607
Geom File=g01
Flow File=f01
Subcritical Flow
K Sum by GR= 0
Std Step Tol= 0.01
Critical Tol= 0.01
Num of Std Step Trials= 20
Max Error Tol= 0.3
Flow Tol Ratio= 0.001
Split Flow NTrial= 30
Split Flow Tol= 0.02
Split Flow Ratio= 0.02
Log Output Level= 0
Friction Slope Method= 1
Unsteady Friction Slope Method= 2
Unsteady Bridges Friction Slope Method= 1
Parabolic Critical Depth
Global Vel Dist= 0 , 0 , 0
Global Log Level= 0
CheckData=True
Encroach Param=-1 ,0,0, 0
Computation Interval=1HOUR
Output Interval=1HOUR
Run HTab= 0
Run UNet= 0
Run PostProcess= 0
UNET Theta= 1
UNET Theta Warmup= 1
UNET ZTol= 0.02
UNET ZSATol= 0.1
UNET MxIter= 20
UNET MaxInSteps= 20
UNET DtIC= 0
UNET DtMin= 0
UNET MaxCRTS= 20
UNET WFStab= 2
UNET SFStab= 1
UNET WFX= 1
UNET SFX= 1
UNET DSS MLevel= 4
UNET DZMax Abort= 100
UNET Convert EG Bridges=-1
UNET Use Existing IB Tables=-1
UNET Froude Reduction=False
UNET Froude Limit= 1
UNET Froude Power= 10
Instantaneous Interval=1HOUR
Write IC File= 0
Echo Input=False
Echo Output=False
Write Detailed= 0
Detailed Automatic Start=False, 10

--- W142-00-00.p03 (plan) ---

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Plan Title=Floodway
Version=Version 3.0.1  Mar 2001
Short Identifier=Floodway0607
Geom File=g01
Flow File=f03
Encroach Param=-1 ,0,0, 2
Encroach River=W142-00-00
Encroach Reach=Reach - 1
Encroach Node=6627.7
       1  4951.3  5039.3
Encroach Node=6168.5
       1  4962.9  5037.3
Encroach Node=5524.9
       1  4962.9  5037.3
Encroach Node=4879.4
       1  4931.4  5037.3
Encroach Node=4525.0
       1  4962.9  5037.3
Encroach Node=4466.0
       1  4962.9  5037.3
Encroach Node=4407.0
       1  4962.9  5037.3
Encroach Node=4039.2
       1  4961.1    5028
Encroach Node=3338.3
       1  4961.1    5028
Encroach Node=2616.2
       1  4949.5  5079.5
Encroach Node=2344.5
       1 4957.69 5044.94
Encroach Node=2146.0
       1 4957.69 5044.94
Encroach Node=2094.2
       1 4957.69 5044.94
Encroach Node=2042.4
       1 4957.69 5044.94
Encroach Node=1827.1
       1 4957.69 5044.94
Encroach Node=1033.0
       1  4959.8  5057.8
Encroach Node=246.9
       1  4947.9  5070.7
Encroach Reach=W142-00-00_0002
Encroach Node=6627.7
       1  4951.3  5039.3
Encroach Node=6168.5
       1  4962.9  5037.3
Encroach Node=5524.9
       1  4962.9  5037.3
Encroach Node=4879.4
       1  4931.4  5037.3
Encroach Node=4525.0
       1  4962.9  5037.3
Encroach Node=4466.0
       1  4962.9  5037.3
Encroach Node=4407.0
       1  4962.9  5037.3
Encroach Node=4039.2
       1  4961.1    5028
Encroach Node=3338.3
       1  4961.1    5028
Encroach Node=2616.2
       1  4949.5  5079.5
Encroach Node=2344.5
       1 4957.69 5044.94
Encroach Node=2146.0
       1 4957.69 5044.94
Encroach Node=2094.2
       1 4957.69 5044.94
Encroach Node=2042.4
       1 4957.69 5044.94
Encroach Node=1827.1
       1 4957.69 5044.94
Encroach Node=1033.0
       1  4959.8  5057.8
Encroach Node=246.9
       1  4947.9  5070.7
DSS File=dss
IC Time=0
Write Velocity= 0

--- W142-00-00.f01 (steady flow) ---

Flow Title=FEMA Effective June 2007
Program Version=3.13
Number of Profiles= 4
Profile Names=10PCT_10yr,2PCT_50yr,1PCT_100yr,0.2PCT_500yr
River Rch & RM=W142-00-00,W142-00-00_0002 ,6627.7
     252     381     449     653
River Rch & RM=W142-00-00,W142-00-00_0002 ,4525
     308     466     549     798
River Rch & RM=W142-00-00,W142-00-00_0002 ,4466
     311     471     555     807
River Rch & RM=W142-00-00,W142-00-00_0002 ,3338.3
     357     540     636     925
River Rch & RM=W142-00-00,W142-00-00_0002 ,2146
     409     619     729    1060
River Rch & RM=W142-00-00,W142-00-00_0002 ,1033
     416     630     742    1079
River Rch & RM=W142-00-00,W142-00-00_0002 ,246.9
     437     661     779    1133
Boundary for River Rch & Prof#=W142-00-00,W142-00-00_0002 , 1
Up Type= 0
Dn Type= 3
Dn Slope=0.0084
Boundary for River Rch & Prof#=W142-00-00,W142-00-00_0002 , 2
Up Type= 0
Dn Type= 3
Dn Slope=0.0084
Boundary for River Rch & Prof#=W142-00-00,W142-00-00_0002 , 3
Up Type= 0
Dn Type= 3
Dn Slope=0.0084
Boundary for River Rch & Prof#=W142-00-00,W142-00-00_0002 , 4
Up Type= 0
Dn Type= 3
Dn Slope=0.0084
DSS Import GetInterval= 0
DSS Import GetPeak= 0
DSS Import FillOption= 0

--- W142-00-00.f03 (steady flow) ---

Flow Title=Floodway
Program Version=3.13
Number of Profiles= 2
Profile Names=1PCT_100_YR,1PCT_Floodway_100yrFW
River Rch & RM=W142-00-00,W142-00-00_0002       ,6627.7
     449     449
River Rch & RM=W142-00-00,W142-00-00_0002       ,4525
     549     549
River Rch & RM=W142-00-00,W142-00-00_0002       ,4466
     555     555
River Rch & RM=W142-00-00,W142-00-00_0002       ,3338.3
     636     636
River Rch & RM=W142-00-00,W142-00-00_0002       ,2146
     729     729
River Rch & RM=W142-00-00,W142-00-00_0002       ,1033
     742     742
River Rch & RM=W142-00-00,W142-00-00_0002       ,246.9
     779     779
Boundary for River Rch & Prof#=W142-00-00,W142-00-00_0002       , 1
Up Type= 0
Dn Type= 3
Dn Slope=0.0084
Boundary for River Rch & Prof#=W142-00-00,W142-00-00_0002       , 2
Up Type= 0
Dn Type= 1
Dn Known WS=35.76
DSS Import GetInterval= 0
DSS Import GetPeak= 0
DSS Import FillOption= 0

--- W142-00-00.g01 (geometry) ---

Geom Title=W142-00-00 June 2007
Version=Version 3.0.1  Mar 2001

River Reach=W142-00-00      ,W142-00-00_0002
Reach XY= 30
      3080351.39     13834699.61      3080340.21      13835147.5
       3080321.3     13835551.15      3080317.71     13835755.48
      3080318.66     13835948.33       3080307.8     13836135.76
      3080296.93     13836502.46       3080291.5     13836779.52
      3080276.49     13836881.09      3080274.08      13837203.8
      3080267.52     13837451.07      3080231.68     13838307.83
      3080224.51     13838908.28      3080210.01     13839183.46
      3080210.01      13839571.9      3080213.75     13839874.37
      3080220.88     13839990.21      3080217.34     13840075.12
      3080221.43     13840134.27        3080221.       13840323.
      3080217.34     13840394.16      3080215.44     13840484.58
      3080207.29      13840571.5      3080210.01     13840701.89
      3080199.15     13840818.69      3080182.85     13840875.73
       3080142.1      13840938.2      3080113.75       13840983.
      3080068.25       13841035.      3080006.25       13841087.

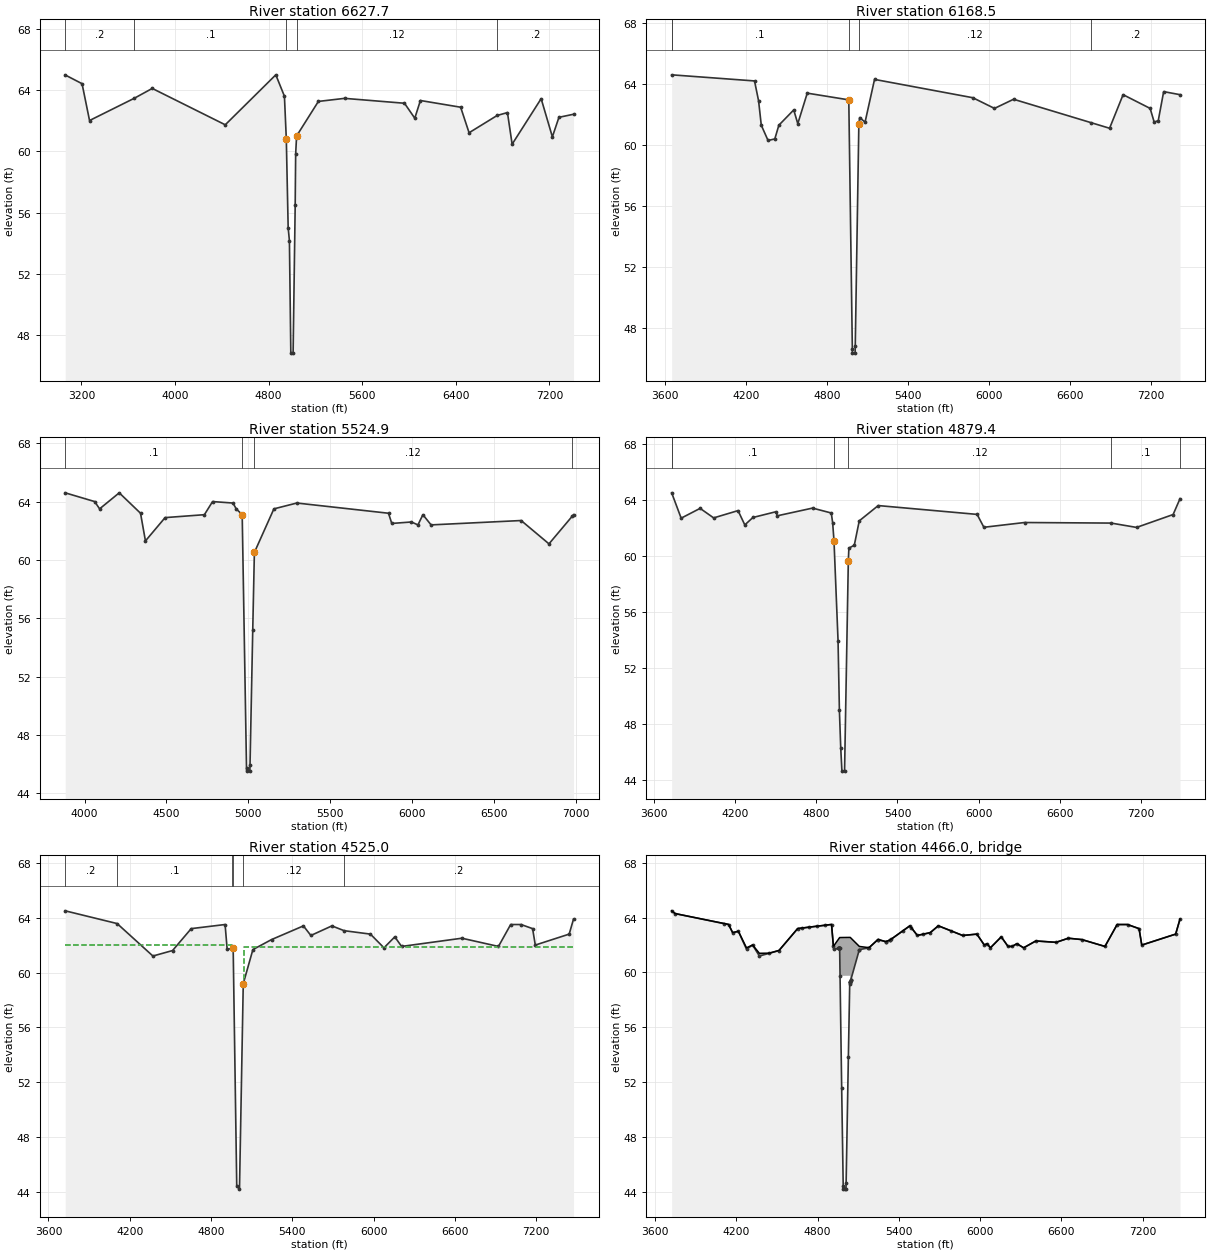
Type RM Length L Ch R = 1 ,6627.7  ,457.2,459.2,459.5
BEGIN DESCRIPTION:
Cross Section 6627.7-Interpolated
END DESCRIPTION:
XS GIS Cut Line= 5
      3078416.34      13834585.6      3080222.73     13834694.22
      3080400.28     13834701.62      3080511.07     13834682.01
       3082754.8     13834752.12
#Sta/Elev= 30
  3061.6      65  3205.6   64.43  3269.6   62.02    3653   63.48  3805.6   64.12
  4429.6   61.74  4861.6   65.01  4935.3   63.61  4951.3   60.83  4967.3      55
  4977.9   54.16  4989.9   46.83  5009.5    46.8  5027.3   56.47  5031.3   59.82
  5039.3   61.01  5225.5   63.27  5449.5   63.47  5961.5   63.15  6049.5   62.17
  6097.5   63.33  6441.5   62.89  6513.5   61.22  6753.3   62.35  6841.5   62.54
  6881.5   60.47  7129.5   63.45  7225.5   60.95  7281.5   62.23  7406.3   62.43
#Mann= 5 , 1 , 0
  3061.6      .2       0    3653      .1       0  4951.3    .015       0
  5039.3     .12       0  6753.3      .2       0
Bank Sta=4951.3,5039.3
XS Rating Curve= 0
Exp/Cntr=.3,.1

Type RM Length L Ch R = 1 ,6168.5  ,646.9,643.6,641
BEGIN DESCRIPTION:
Cross Section 6168.5-Interpolated
END DESCRIPTION:
XS GIS Cut Line= 6
      3079027.11     13835052.89      3079562.01     13834960.95
      3080046.76     13835111.39      3080564.93     13835194.97
      3081517.71      13835228.4      3082748.45     13835219.06
#Sta/Elev= 30
    3653    64.6  4265.7    64.2  4295.7    62.9  4315.7    61.3  4365.7    60.3
  4415.7    60.4  4445.7    61.3  4555.7    62.3  4585.7    61.4  4655.7    63.4
  4962.9   62.96  4989.2   46.61  4989.9    46.4  5009.5   46.37  5010.7   46.81
  5037.3   61.37  5043.3    61.8  5083.3    61.5  5153.3    64.3  5880.3    63.1
  6040.3    62.4  6181.6      63  6753.3   61.47  6891.6    61.1  6991.6    63.3
  7191.6    62.4  7221.6    61.5  7251.6    61.6  7291.6    63.5  7412.4    63.3
#Mann= 5 , 1 , 0
    3653      .2       0    3653      .1       0  4962.9    .015       0
  5037.3     .12       0  6753.3      .2       0
Bank Sta=4962.9,5037.3
XS Rating Curve= 0
Exp/Cntr=.3,.1

Type RM Length L Ch R = 1 ,5524.9  ,650.3,645.5,643.4
BEGIN DESCRIPTION:
Cross Section 5524.9-Interpolated
END DESCRIPTION:
XS GIS Cut Line= 4
      3079203.78      13835709.4      3080224.58     13835796.07
      3080613.73     13835819.65      3082302.84     13835876.59
#Sta/Elev= 30
    3882    64.6    4062      64    4092    63.5    4212    64.6    4342    63.2
    4372    61.3    4492    62.9    4732    63.1    4782      64  4906.5    63.9
  4926.5    63.5  4962.9    63.1  4989.2   45.75  4989.9   45.54  5009.5   45.51
  5010.7   45.95  5027.3   55.18  5037.3   60.51  5156.5    63.5  5296.4    63.9
  5856.4    63.2  5876.4    62.5  5996.4    62.6  6036.4    62.4  6066.4    63.1
  6116.4    62.4  6666.4    62.7  6836.4    61.1  6978.8      63  6986.4    63.1
#Mann= 4 , 1 , 0
    3882      .1       0  4962.9    .015       0  5037.3     .12       0
  6978.8      .1       0
Bank Sta=4962.9,5037.3
XS Rating Curve= 0
Exp/Cntr=.3,.1

Type RM Length L Ch R = 1 ,4879.4  ,356,354.4,353.5
BEGIN DESCRIPTION:
Cross Section 4879.4-Interpolated
END DESCRIPTION:
XS GIS Cut Line= 5
      3079031.77     13836465.77      3080199.97     13836446.82
      3080396.73     13836446.82      3082403.93     13836461.05
      3082773.27     13836553.93
#Sta/Elev= 30
    3733   64.52    3803   62.71    3943   63.41    4043   62.73    4223   63.25
    4273   62.23    4333   62.76    4503   63.17    4513   62.88    4773   63.43
  4911.4   63.08  4921.4    62.4  4931.4   61.11  4961.4   53.97  4971.4   48.98
  4981.4   46.28  4989.9   44.68  5009.5   44.65  5037.3   59.65  5041.4   60.57
  5081.4   60.78  5118.1   62.52  5258.1   63.61  5988.1   62.98  6038.1   62.06
  6338.1    62.4  6977.8   62.36  7165.4   62.05  7435.4   62.97  7486.2    64.1
#Mann= 6 , 1 , 0
    3733      .2       0    3733      .1       0  4931.4    .015       0
  5037.3     .12       0  6977.8      .1       0  7486.2      .2       0
Bank Sta=4931.4,5037.3
XS Rating Curve= 0
Exp/Cntr=.5,.3

Type RM Length L Ch R = 1 ,4525.0  ,118,118,118
BEGIN DESCRIPTION:
Upstream Section of Bridge/Culvert/Weir
END DESCRIPTION:
XS GIS Cut Line= 6
      3079028.64     13836973.04      3079970.27     13836802.39
      3080863.54     13836829.14      3081251.21     13836877.12
      3081924.59     13836812.44      3082753.86     13836829.16
#Sta/Elev= 30
  3723.4   64.51  4106.5   63.58  4370.6   61.21  4515.6   61.61  4653.2   63.21
  4903.2   63.51  4918.6    61.7  4952.3   61.76  4962.9   61.78  4989.2   44.43
  5009.5   44.19  5037.3   59.19  5108.4   61.68  5245.9   62.41  5481.2   63.41
  5536.2   62.71  5691.2   63.41  5781.8   63.06  5975.6   62.81  6075.6   61.81
  6155.6   62.61  6205.6   61.91  6650.6   62.51  6920.6   61.91  7010.6   63.51
  7087.4   63.51  7172.4   63.21  7192.4   62.01  7442.4   62.81  7474.5   63.91
#Mann= 6 , 1 , 0
  3723.4      .2       0  4106.5      .1       0  4952.3     .12       0
  4962.9    .015       0  5037.3     .12       0  5781.8      .2       0
#XS Ineff= 2 , 0
       0    4956      62    5044       0    61.9
Permanent Ineff=
       F       F
Bank Sta=4962.9,5037.3
XS Rating Curve= 0
Exp/Cntr=.5,.3

Type RM Length L Ch R = 3 ,4466.0  ,,,
BEGIN DESCRIPTION:
SAN FELIPE
Structure ID: W42-4
END DESCRIPTION:
Bridge Culvert--1,0,-1,-1, 0
Deck Dist Width WeirC Skew NumUp NumDn MinLoCord MaxHiCord MaxSubmerge Is_Ogee
10,98,2.6,0, 49, 49, , , .95, 0, 1,1,,
  3723.4  3748.4  4143.4  4173.4  4215.6  4275.6  4320.6  4370.6  4443.8  4515.6
  4653.2  4903.2  4916.3  4918.6  4962.9  4965.9 5040.89    5041  5041.1  5108.4
  5179.6  5245.9  5304.7  5335.9  5481.2  5536.2  5631.2  5691.2  5870.6  5975.6
  6030.6  6050.6  6075.6  6155.6  6205.6  6235.6  6270.6  6320.6  6410.6  6560.6
  6650.6  6750.6  6920.6  7010.6  7087.4  7172.4  7192.4  7442.4  7474.5
    64.5    64.3   63.51   62.91   63.01    61.8   62.01    61.4   61.41   61.61
   63.21   63.51   61.97   61.93   62.55   62.55   62.56   62.56   62.56    61.9
   61.81   62.41   62.25   62.38   63.41   62.71   62.91   63.41    62.7    62.8
      62    62.1    61.8    62.6    61.9    61.9    62.1    61.8    62.3    62.2
    62.5    62.4    61.9    63.5    63.5    63.2      62    62.8    63.9
    64.5    64.3    63.5    62.9      63    61.7      62    61.2    61.4    61.6
    63.2    63.5   61.96   61.69   61.77   59.75   59.76   59.31   59.31   61.67
    61.8    62.4   62.24   62.37    63.4    62.7    62.9    63.4    62.7    62.8
      62    62.1    61.8    62.6    61.9    61.9    62.1    61.8    62.3    62.2
    62.5    62.4    61.9    63.5    63.5    63.2      62    62.8    63.9
  3723.4  3748.4  4143.4  4173.4  4215.6  4275.6  4320.6  4370.6  4443.8  4515.6
  4653.2  4903.2  4916.3  4918.6  4962.9  4965.9 5040.89    5041  5041.1  5108.4
  5179.6  5245.9  5304.7  5335.9  5481.2  5536.2  5631.2  5691.2  5870.6  5975.6
  6030.6  6050.6  6075.6  6155.6  6205.6  6235.6  6270.6  6320.6  6410.6  6560.6
  6650.6  6750.6  6920.6  7010.6  7087.4  7172.4  7192.4  7442.4  7474.5
    64.5    64.3   63.51   62.91   63.01    61.8   62.01    61.4   61.41   61.61
   63.21   63.51   61.97   61.93   62.55   62.55   62.56   62.56   62.56    61.9
   61.81   62.41   62.25   62.38   63.41   62.71   62.91   63.41    62.7    62.8
      62    62.1    61.8    62.6    61.9    61.9    62.1    61.8    62.3    62.2
    62.5    62.4    61.9    63.5    63.5    63.2      62    62.8    63.9
    64.5    64.3    63.5    62.9      63    61.7      62    61.2    61.4    61.6
    63.2    63.5   61.96   61.69   61.77   59.75   59.76   59.31   59.31   61.67
    61.8    62.4   62.24   62.37    63.4    62.7    62.9    63.4    62.7    62.8
      62    62.1    61.8    62.6    61.9    61.9    62.1    61.8    62.3    62.2
    62.5    62.4    61.9    63.5    63.5    63.2      62    62.8    63.9
BR Coef= 1 , 1 , 0 ,1.25, 0 ,,,.8,0,2,0,
WSPro=,,,, 1 ,,,, 0 ,,,, 0 ,,,,-1 ,-1 ,-1 , 0 , 0 , 0 , 0 , 0
BR U #Sta/Elev= 84
  3723.4    64.5  3748.4    64.3  4106.5   63.57  4143.4    63.5  4173.4    62.9
  4215.6      63  4275.6    61.7  4320.6      62  4370.6    61.2  4443.8    61.4
  4515.6    61.6  4653.2    63.2  4682.1   63.23  4734.7    63.3  4793.8   63.37
  4855.2   63.44  4903.2    63.5  4916.3   61.96  4918.6   61.69  4952.3   61.75
 4960.59   61.77  4960.7   61.77 4960.81   61.77  4961.4   61.77 4961.51   61.77
  4961.6   61.77  4961.7   61.77  4962.9   61.77  4965.9   59.73  4977.9   51.54
  4989.2   44.42  4989.9   44.21  4999.5   44.22  5009.5   44.18  5010.7   44.62
  5027.3   53.85  5037.3   59.18  5040.8    59.3 5040.89   59.31    5041   59.31
  5041.1   59.31 5044.19   59.42  5044.3   59.43 5044.41   59.43  5108.4   61.67
  5109.2   61.67  5174.8   61.79  5179.6    61.8  5242.3   62.37  5245.9    62.4
  5304.7   62.24  5306.1   62.25  5332.7   62.36  5335.9   62.37  5342.7   62.42
  5432.7   63.06  5481.2    63.4  5492.7   63.25  5536.2    62.7  5576.1   62.78
  5631.2    62.9  5691.2    63.4  5781.8   63.05  5870.6    62.7  5975.6    62.8
  6030.6      62  6050.6    62.1  6075.6    61.8  6155.6    62.6  6205.6    61.9
  6235.6    61.9  6270.6    62.1  6320.6    61.8  6410.6    62.3  6560.6    62.2
  6650.6    62.5  6750.6    62.4  6920.6    61.9  7010.6    63.5  7087.4    63.5
  7172.4    63.2  7192.4      62  7442.4    62.8  7474.5    63.9
BR U #Mann= 6
  3723.4      .2  4106.5      .1  4952.3     .12  4962.9    .015  5037.3     .12
  5781.8      .2
BR U Banks=4962.9,5037.3
BR D #Sta/Elev= 84
  3723.4    64.5  3748.4    64.3  4106.5   63.57  4143.4    63.5  4173.4    62.9
  4215.6      63  4275.6    61.7  4320.6      62  4370.6    61.2  4443.8    61.4
  4515.6    61.6  4653.2    63.2  4682.1   63.23  4734.7    63.3  4793.8   63.37
  4855.2   63.44  4903.2    63.5  4916.3   61.96  4918.6   61.69  4952.3   61.75
 4960.59   61.77  4960.7   61.77 4960.81   61.77  4961.4   61.77 4961.51   61.77
  4961.6   61.77  4961.7   61.77  4962.9   61.77  4965.9   59.73  4977.9   51.54
  4989.2   44.42  4989.9   44.21  4999.5   44.22  5009.5   44.18  5010.7   44.62
  5027.3   53.85  5037.3   59.18  5040.8    59.3 5040.89   59.31    5041   59.31
  5041.1   59.31 5044.19   59.42  5044.3   59.43 5044.41   59.43  5108.4   61.67
  5109.2   61.67  5174.8   61.79  5179.6    61.8  5242.3   62.37  5245.9    62.4
  5304.7   62.24  5306.1   62.25  5332.7   62.36  5335.9   62.37  5342.7   62.42
  5432.7   63.06  5481.2    63.4  5492.7   63.25  5536.2    62.7  5576.1   62.78
  5631.2    62.9  5691.2    63.4  5781.8   63.05  5870.6    62.7  5975.6    62.8
  6030.6      62  6050.6    62.1  6075.6    61.8  6155.6    62.6  6205.6    61.9
  6235.6    61.9  6270.6    62.1  6320.6    61.8  6410.6    62.3  6560.6    62.2
  6650.6    62.5  6750.6    62.4  6920.6    61.9  7010.6    63.5  7087.4    63.5
  7172.4    63.2  7192.4      62  7442.4    62.8  7474.5    63.9
BR D #Mann= 6
  3723.4      .2  4106.5      .1  4952.3     .12  4962.9    .015  5037.3     .12
  5781.8      .2
BR D Banks=4962.9,5037.3
BC Design=,, 0 ,, 0 ,,,,,,
BC HTab HWMax=64.51

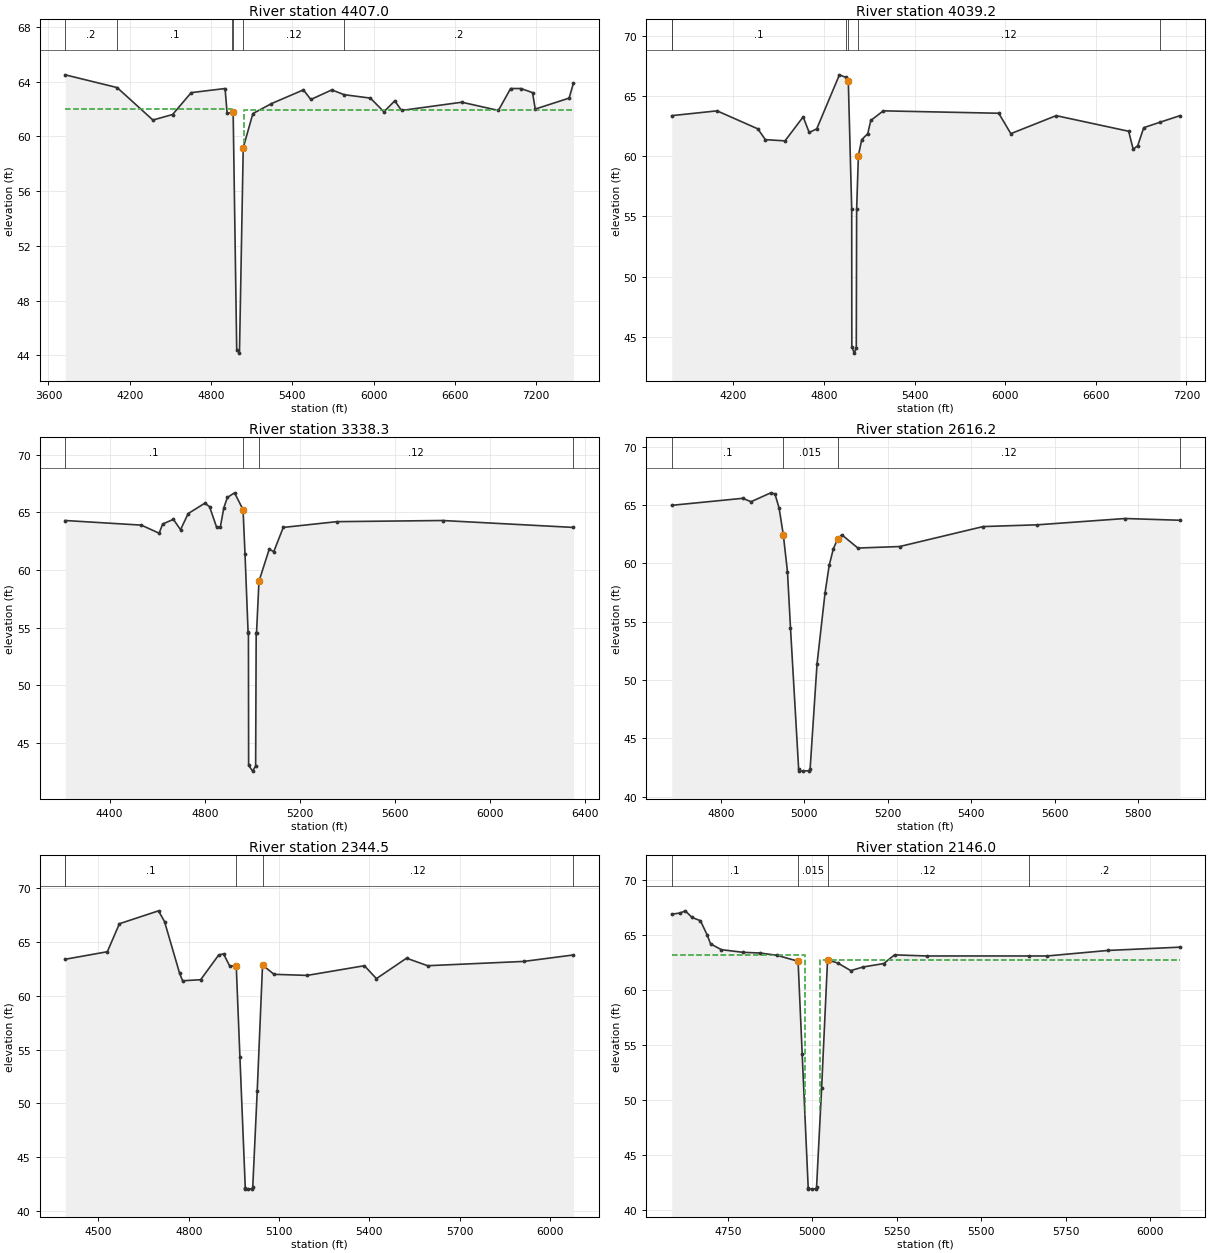
Type RM Length L Ch R = 1 ,4407.0  ,367.8,367.8,367.8
BEGIN DESCRIPTION:
Downstream Section of Bridge/Culvert/Weir
END DESCRIPTION:
XS GIS Cut Line= 6
      3079011.39     13837089.77      3079953.01     13836919.13
      3080846.28     13836945.88      3081233.95     13836993.86
      3081907.33     13836929.18      3082736.61     13836945.89
#Sta/Elev= 30
  3723.4   64.49  4106.5   63.56  4370.6   61.19  4515.6   61.59  4653.2   63.19
  4903.2   63.49  4918.6   61.68  4952.3   61.74  4962.9   61.76  4989.2   44.41
  5009.5   44.17  5037.3   59.17  5108.4   61.66  5245.9   62.39  5481.2   63.39
  5536.2   62.69  5691.2   63.39  5781.8   63.04  5975.6   62.79  6075.6   61.79
  6155.6   62.59  6205.6   61.89  6650.6   62.49  6920.6   61.89  7010.6   63.49
  7087.4   63.49  7172.4   63.19  7192.4   61.99  7442.4   62.79  7474.5   63.89
#Mann= 6 , 1 , 0
  3723.4      .2       0  4106.5      .1       0  4952.3     .12       0
  4962.9    .015       0  5037.3     .12       0  5781.8      .2       0
#XS Ineff= 2 , 0
       0    4956      62    5044       0    61.9
Permanent Ineff=
       F       F
Bank Sta=4962.9,5037.3
XS Rating Curve= 0
Exp/Cntr=.5,.3

Type RM Length L Ch R = 1 ,4039.2  ,700,700.9,702.5
BEGIN DESCRIPTION:
Cross Section 4039.2-Interpolated
END DESCRIPTION:
XS GIS Cut Line= 6
      3079064.18     13837269.22      3080201.94     13837283.81
       3080464.5      13837291.1      3081026.08      13837400.5
      3081208.41      13837400.5      3082418.45     13837393.51
#Sta/Elev= 30
  3792.2    63.4  4092.2    63.8  4362.2    62.3  4412.2    61.4  4542.2    61.3
  4662.2    63.3  4702.2      62  4752.2    62.3  4902.2    66.8  4944.4   66.59
  4961.1   66.29  4983.7   55.62  4984.5   44.13  5001.3   43.62    5014   44.08
  5016.3   55.61    5028   60.08    5050    61.4    5090    61.9    5110      63
  5192.7    63.8  5957.2    63.6  6037.2    61.9  6337.2    63.4  6817.2    62.1
  6847.2    60.6  6877.2    60.9  6917.2    62.4  7021.9   62.84  7157.2    63.4
#Mann= 6 , 1 , 0
  3792.2      .2       0  3792.2      .1       0  4944.4     .12       0
  4961.1    .015       0    5028     .12       0  7021.9      .1       0
Bank Sta=4961.1,5028
XS Rating Curve= 0
Exp/Cntr=.3,.1

Type RM Length L Ch R = 1 ,3338.3  ,721.7,722.1,725.5
BEGIN DESCRIPTION:
Cross Section 3338.3
END DESCRIPTION:
XS GIS Cut Line= 3
      3079464.51      13837893.9      3079950.94     13837967.99
      3081593.07     13838069.62
#Sta/Elev= 30
  4213.2    64.3  4533.2    63.9  4608.2    63.2  4623.2      64  4668.2    64.4
  4698.2    63.5  4730.2    64.9  4800.2    65.8  4820.2    65.5  4850.2    63.7
  4865.2    63.7  4880.2    65.4  4895.2    66.3  4925.2    66.7  4961.1   65.24
  4969.3   61.42  4982.3   54.59  4983.7   54.57  4984.5   43.08  5001.3   42.57
    5014   43.03  5016.3   54.56  5017.8   54.57    5028   59.03  5071.1   61.81
  5090.2    61.6  5130.2    63.7  5355.2    64.2  5800.2    64.3  6350.5    63.7
#Mann= 4 , 1 , 0
  4213.2      .1       0  4961.1    .015       0    5028     .12       0
  6350.5      .2       0
Bank Sta=4961.1,5028
XS Rating Curve= 0
Exp/Cntr=.3,.1

Type RM Length L Ch R = 1 ,2616.2  ,271.5,271.7,272.2
BEGIN DESCRIPTION:
Cross Section 2616.2-Interpolated
END DESCRIPTION:
XS GIS Cut Line= 4
      3079909.25     13838698.48      3080126.49     13838704.12
      3080344.99     13838712.52      3081126.55     13838729.33
#Sta/Elev= 26
  4682.2   64.97  4852.2   65.57  4872.2   65.28  4919.5   66.04  4929.5   65.94
  4939.5   64.72  4949.5   62.44  4959.5   59.27  4966.7   54.47  4986.3   42.34
  4986.8   42.22  4997.2    42.2  5012.1   42.24  5013.7   42.37  5030.2   51.35
  5049.5   57.47  5059.5   59.84  5069.5   61.26  5079.5   62.06  5089.5   62.45
  5128.2   61.31  5228.2   61.44  5428.2   63.15  5558.2    63.3  5768.2   63.84
  5899.9   63.69
#Mann= 4 , 1 , 0
  4682.2      .1       0  4949.5    .015       0  5079.5     .12       0
  5899.9      .2       0
Bank Sta=4949.5,5079.5
XS Rating Curve= 0
Exp/Cntr=.3,.1

Type RM Length L Ch R = 1 ,2344.5  ,180.7,198.5,228.7
BEGIN DESCRIPTION:
Cross Section 2344.5-Interpolated
END DESCRIPTION:
XS GIS Cut Line= 4
      3079633.06      13838822.7       3080136.3     13838975.86
      3080304.04     13838983.15      3081295.93     13839056.08
#Sta/Elev= 28
  4389.4    63.4  4529.4    64.1  4569.4    66.7  4699.4    67.9  4719.4    66.9
  4769.4    62.1  4779.4    61.4  4839.4    61.5  4899.4    63.8  4915.4    63.9
  4935.4    62.8 4957.69   62.74 4969.83   54.31 4987.59   42.18 4988.04   42.06
 4997.46   42.04 5010.96   42.08 5012.41   42.21 5027.36   51.19 5044.94   62.86
  5083.3      62  5193.3    61.9  5383.3    62.8  5423.3    61.6  5523.3    63.5
  5593.3    62.8  5913.3    63.2  6077.9    63.8
#Mann= 5 , 1 , 0
  4389.4      .2       0  4389.4      .1       0 4957.69    .015       0
 5044.94     .12       0  6077.9      .2       0
Bank Sta=4957.69,5044.94
XS Rating Curve= 0
Exp/Cntr=.5,.3

Type RM Length L Ch R = 1 ,2146.0  ,103.6,103.6,103.6
BEGIN DESCRIPTION:
Upstream Section of Bridge/Culvert/Weir
END DESCRIPTION:
XS GIS Cut Line= 3
      3079819.25     13839001.27      3080787.92     13839358.58
      3081232.92     13839518.39
#Sta/Elev= 30
  4583.5   66.91  4608.5   67.01  4623.5   67.21  4643.5   66.61  4668.5   66.31
  4688.5   65.01  4698.5   64.21 4730.47   63.68 4794.79   63.44 4843.99   63.38
  4895.2   63.17 4957.69   62.63 4969.83    54.2 4987.59   42.07 4988.04   41.95
 4997.46   41.93 5010.96   41.97 5012.41    42.1 5027.36   51.08 5044.94   62.75
 5075.11   62.47  5113.7   61.78 5150.21   62.11 5211.37   62.42  5243.4   63.21
  5338.4   63.11  5642.1   63.11  5695.2   63.11  5875.2   63.61  6088.8   63.91
#Mann= 4 , 1 , 0
  4583.5      .1       0 4957.69    .015       0 5044.94     .12       0
  5642.1      .2       0
#XS Ineff= 2 , 0
       0    4978    63.2    5024       0    62.7
Permanent Ineff=
       F       F
Bank Sta=4957.69,5044.94
XS Rating Curve= 0
Exp/Cntr=.5,.3

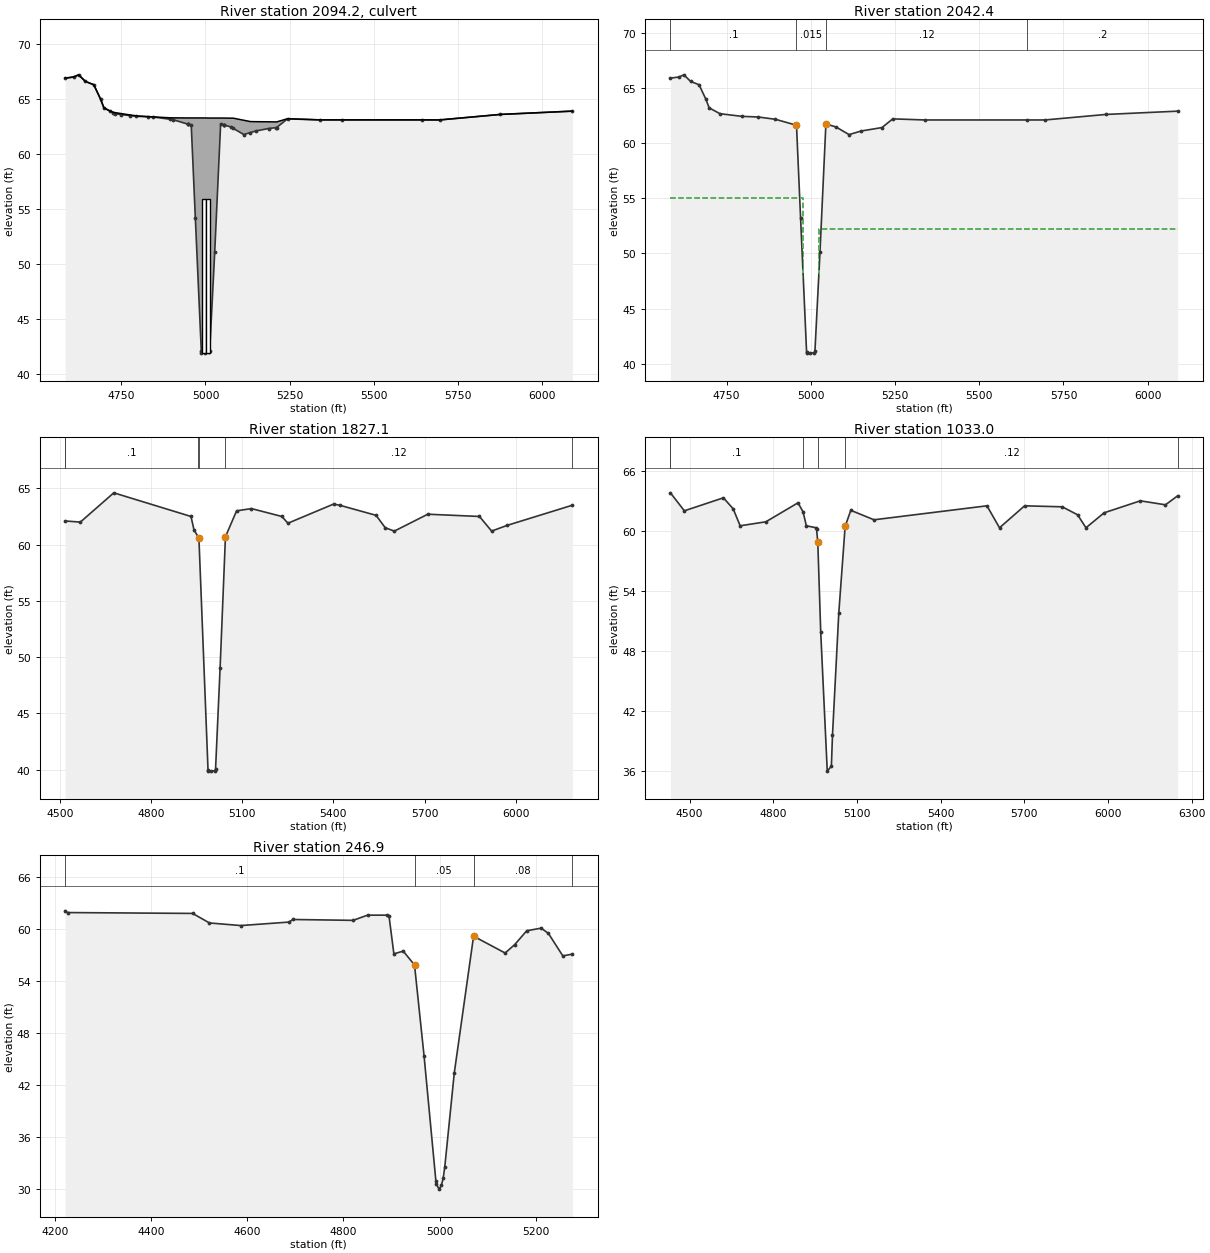
Type RM Length L Ch R = 2 ,2094.2  ,,,
BEGIN DESCRIPTION:
WOODWAY DRIVE, SKEW ANGLE OF 25 DEGREES
Structure ID: W42-3
END DESCRIPTION:
Bridge Culvert--1,0,-1,-1, 0
Deck Dist Width WeirC Skew NumUp NumDn MinLoCord MaxHiCord MaxSubmerge Is_Ogee
10,83.6,3,0, 47, 47, , , .95, 0, 1,1,,
  4583.5  4608.5  4623.5  4643.5  4668.5  4688.5  4698.5    4718  4726.7 4730.47
 4749.04  4774.6 4794.79  4828.8 4843.99  4895.2 4903.78 4948.19  4948.3 4948.41
 4957.69 4969.83 4987.59 4988.04 4997.46 5010.96 5012.41 5027.36 5044.94 5053.89
    5054 5054.11 5075.11  5082.3  5113.7  5133.2 5150.21 5187.54  5209.5 5211.37
  5243.4  5338.4  5406.2  5642.1  5695.2  5875.2  6088.8
    66.9      67    67.2    66.6    66.3      65    64.2   63.89   63.79   63.77
   63.68   63.56   63.47    63.4   63.38   63.29   63.29   63.28   63.28   63.28
   63.28   63.28   63.28   63.28   63.28   63.27   63.27   63.27   63.27   63.27
   63.27   63.27   63.26   63.26   63.07   62.95   62.94   62.93   62.92   62.92
   63.21   63.11   63.11   63.11    63.1    63.6    63.9
    66.9      67    67.2    66.6    66.3      65    64.2   63.88   63.73   63.67
   63.59    63.5   63.43   63.39   63.37   63.16   63.12   62.71   62.71   62.71
   62.62   54.19   42.06   41.94   41.92   41.96   42.09   51.07   62.74   62.66
   62.66   62.65   62.46   62.33   61.77   61.95    62.1   62.32    62.4   62.41
    63.2    63.1    63.1    63.1    63.1    63.6    63.9
  4583.5  4608.5  4623.5  4643.5  4668.5  4688.5  4698.5    4718  4726.7 4730.47
 4749.04  4774.6 4794.79  4828.8 4843.99  4895.2 4903.78 4948.19  4948.3 4948.41
 4957.69 4969.83 4987.59 4988.04 4997.46 5010.96 5012.41 5027.36 5044.94 5053.89
    5054 5054.11 5075.11  5082.3  5113.7  5133.2 5150.21 5187.54  5209.5 5211.37
  5243.4  5338.4  5406.2  5642.1  5695.2  5875.2  6088.8
    66.9      67    67.2    66.6    66.3      65    64.2   63.89   63.79   63.77
   63.68   63.56   63.47    63.4   63.38   63.29   63.29   63.28   63.28   63.28
   63.28   63.28   63.28   63.28   63.28   63.27   63.27   63.27   63.27   63.27
   63.27   63.27   63.26   63.26   63.07   62.95   62.94   62.93   62.92   62.92
   63.21   63.11   63.11   63.11    63.1    63.6    63.9
   65.98   66.08   66.28   65.68   65.38   64.08   63.28   62.96   62.81   62.75
   62.67   62.58   62.51   62.47   62.45   62.24    62.2   61.79   61.79   61.79
    61.7   53.27   41.14   41.02      41   41.04   41.17   50.15   61.82   61.74
   61.74   61.73   61.54   61.41   60.85   61.03   61.18    61.4   61.48   61.49
   62.28   62.18   62.18   62.18   62.18   62.68   62.98
BR Coef= 1 , 0 , 0 ,1.25, 0 ,,,.8,-1,2,0,
WSPro=,,,, 1 ,,,, 0 ,,,, 0 ,,,,-1 ,-1 ,-1 , 0 , 0 , 0 , 0 , 0
Culvert=2,14,12,83.6,.015,.4,1,8,1,41.9,4995,41.6,4995,Culvert #1  , 0 ,10
Culvert Bottom n=.015
Culvert=2,14,12,83.6,.015,.4,1,8,1,41.9,5008.3,41.6,5008.3,Culvert #2  , 0 ,10
Culvert Bottom n=.015
BR U #Sta/Elev= 47
  4583.5    66.9  4608.5      67  4623.5    67.2  4643.5    66.6  4668.5    66.3
  4688.5      65  4698.5    64.2    4718   63.88  4726.7   63.73 4730.47   63.67
 4749.04   63.59  4774.6    63.5 4794.79   63.43  4828.8   63.39 4843.99   63.37
  4895.2   63.16 4903.78   63.12 4948.19   62.71  4948.3   62.71 4948.41   62.71
 4957.69   62.62 4969.83   54.19 4987.59   42.06 4988.04   41.94 4997.46   41.92
 5010.96   41.96 5012.41   42.09 5027.36   51.07 5044.94   62.74 5053.89   62.66
    5054   62.66 5054.11   62.65 5075.11   62.46  5082.3   62.33  5113.7   61.77
  5133.2   61.95 5150.21    62.1 5187.54   62.32  5209.5    62.4 5211.37   62.41
  5243.4    63.2  5338.4    63.1  5406.2    63.1  5642.1    63.1  5695.2    63.1
  5875.2    63.6  6088.8    63.9
BR U #Mann= 4
  4583.5      .1 4957.69    .015 5044.94     .12  5642.1      .2
BR U Banks=4957.69,5044.94
BR D #Sta/Elev= 47
  4583.5   65.98  4608.5   66.08  4623.5   66.28  4643.5   65.68  4668.5   65.38
  4688.5   64.08  4698.5   63.28    4718   62.96  4726.7   62.81 4730.47   62.75
 4749.04   62.67  4774.6   62.58 4794.79   62.51  4828.8   62.47 4843.99   62.45
  4895.2   62.24 4903.78    62.2 4948.19   61.79  4948.3   61.79 4948.41   61.79
 4957.69    61.7 4969.83   53.27 4987.59   41.14 4988.04   41.02 4997.46      41
 5010.96   41.04 5012.41   41.17 5027.36   50.15 5044.94   61.82 5053.89   61.74
    5054   61.74 5054.11   61.73 5075.11   61.54  5082.3   61.41  5113.7   60.85
  5133.2   61.03 5150.21   61.18 5187.54    61.4  5209.5   61.48 5211.37   61.49
  5243.4   62.28  5338.4   62.18  5406.2   62.18  5642.1   62.18  5695.2   62.18
  5875.2   62.68  6088.8   62.98
BR D #Mann= 4
  4583.5      .1 4957.69    .015 5044.94     .12  5642.1      .2
BR D Banks=4957.69,5044.94
BC Design=,, 0 ,, 0 ,,,,,,
BC HTab HWMax=67.21

Type RM Length L Ch R = 1 ,2042.4  ,215.3,215.3,215.3
BEGIN DESCRIPTION:
Downstream Section of Bridge/Culvert/Weir
END DESCRIPTION:
XS GIS Cut Line= 3
      3079819.25     13839104.87      3080787.92     13839462.18
      3081232.92     13839621.99
#Sta/Elev= 30
  4583.5   65.93  4608.5   66.03  4623.5   66.23  4643.5   65.63  4668.5   65.33
  4688.5   64.03  4698.5   63.23 4730.47    62.7 4794.79   62.46 4843.99    62.4
  4895.2   62.19 4957.69   61.65 4969.83   53.22 4987.59   41.09 4988.04   40.97
 4997.46   40.95 5010.96   40.99 5012.41   41.12 5027.36    50.1 5044.94   61.77
 5075.11   61.49  5113.7    60.8 5150.21   61.13 5211.37   61.44  5243.4   62.23
  5338.4   62.13  5642.1   62.13  5695.2   62.13  5875.2   62.63  6088.8   62.93
#Mann= 4 , 1 , 0
  4583.5      .1       0 4957.69    .015       0 5044.94     .12       0
  5642.1      .2       0
#XS Ineff= 2 , 0
       0    4978      55    5024       0    52.2
Permanent Ineff=
       F       F
Bank Sta=4957.69,5044.94
XS Rating Curve= 0
Exp/Cntr=.5,.3

Type RM Length L Ch R = 1 ,1827.1  ,805,794.1,785
BEGIN DESCRIPTION:
Cross Section 1827.1-Interpolated
END DESCRIPTION:
XS GIS Cut Line= 4
      3079727.87     13839486.39      3080121.71     13839493.68
      3080340.51     13839500.98      3081376.16     13839705.19
#Sta/Elev= 28
  4517.7    62.1  4567.7      62  4677.7    64.6  4931.6    62.5  4941.6    61.3
  4955.1    60.7 4957.69   60.58 4987.59   40.02 4988.04    39.9 4997.46   39.88
 5010.96   39.92 5012.41   40.05 5027.36   49.03 5044.94    60.7  5081.6      63
  5130.5    63.2  5230.5    62.5  5250.5    61.9  5400.5    63.6  5420.5    63.5
  5540.5    62.6  5570.5    61.5  5600.5    61.2  5710.5    62.7  5880.5    62.5
  5920.5    61.2  5970.5    61.7  6186.1    63.5
#Mann= 6 , 1 , 0
  4517.7      .2       0  4517.7      .1       0  4955.1     .12       0
 4957.69    .015       0 5044.94     .12       0  6186.1      .2       0
Bank Sta=4957.69,5044.94
XS Rating Curve= 0
Exp/Cntr=.3,.1

Type RM Length L Ch R = 1 ,1033.0  ,738.8,786.1,838.4
BEGIN DESCRIPTION:
Cross Section 1033.0
END DESCRIPTION:
XS GIS Cut Line= 4
      3079672.53     13840207.45      3079996.49     13840318.07
      3080316.51     13840278.56      3081470.13     13840286.46
#Sta/Elev= 30
  4431.4    63.8  4481.4      62  4621.4    63.3  4656.4    62.2  4681.4    60.5
  4773.7    60.9  4888.7    62.8    4907    61.9  4918.7    60.5  4952.7   60.31
  4955.4   60.15  4959.8   58.84  4970.3   49.84  4993.7   35.94  5008.5   36.44
  5012.4   39.52    5035   51.75  5057.8   60.44  5078.1   62.05  5161.2    61.1
  5566.2    62.5  5611.2    60.3  5701.2    62.5  5836.2    62.4  5891.2    61.6
  5921.2    60.3  5986.2    61.8  6116.2      63  6206.2    62.6  6249.8    63.5
#Mann= 6 , 1 , 0
  4431.4      .2       0  4431.4      .1       0    4907     .12       0
  4959.8     .05       0  5057.8     .12       0  6249.8      .2       0
Bank Sta=4959.8,5057.8
XS Rating Curve= 0
Exp/Cntr=.3,.1

Type RM Length L Ch R = 1 ,246.9   ,0,0,0
BEGIN DESCRIPTION:
Cross Section 246.9
END DESCRIPTION:
XS GIS Cut Line= 5
       3079711.2     13840350.58      3079901.68     13840784.26
      3079992.54     13840962.05      3080154.52     13841120.08
       3080308.6     13841135.88
#Sta/Elev= 30
  4221.6    62.1  4226.6    61.9  4486.6    61.8  4521.6    60.7  4586.6    60.4
  4686.6    60.8  4695.2    61.1  4820.2      61  4850.2    61.6  4890.2    61.6
  4894.9    61.5    4905   57.13  4924.4   57.45  4947.9   55.85  4967.7   45.38
  4992.4   30.87  4993.5   30.52    4999   29.97  5003.8   30.39  5007.5   31.24
  5010.9   32.57  5030.6   43.39  5070.7   59.17  5136.3   57.23  5156.2    58.2
  5181.2    59.8  5211.2    60.1  5226.2    59.5  5256.2    56.9  5276.1    57.1
#Mann= 4 , 1 , 0
  4221.6      .1       0  4947.9     .05       0  5070.7     .08       0
  5276.1      .2       0
Bank Sta=4947.9,5070.7
XS Rating Curve= 0
Exp/Cntr=.3,.1

Chan Stop Cuts=-1